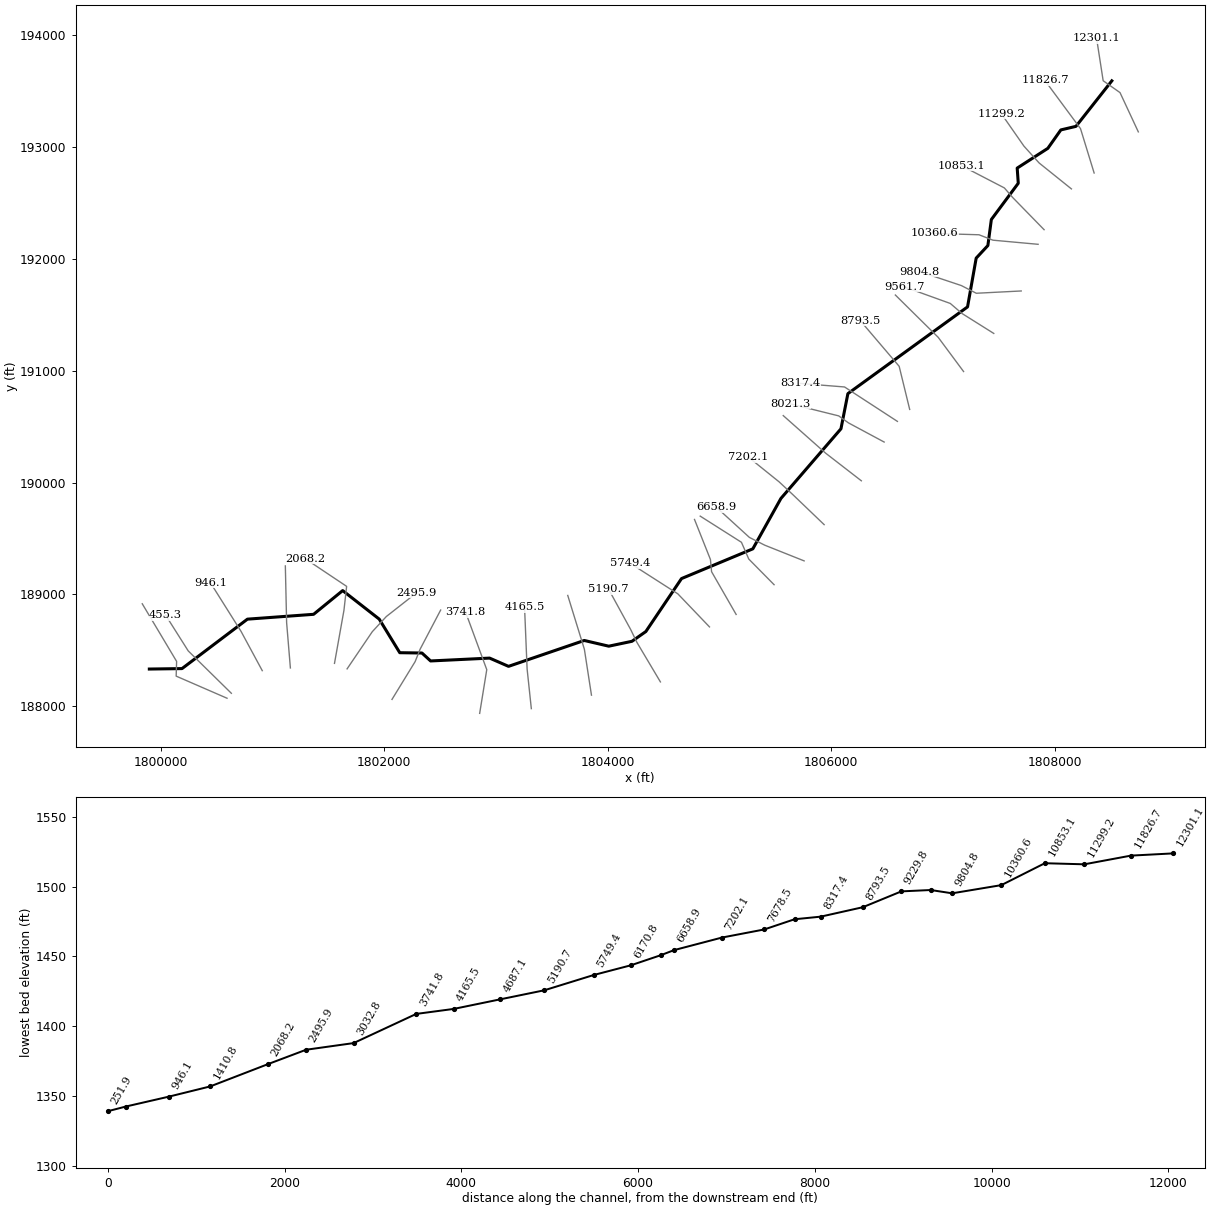
--- NancyFk.prj (project) ---

Proj Title=NancyFk
Current Plan=p01
Default Exp/Contr=0,0
English Units
Geom File=g01
Flow File=f01
Plan File=p01
BEGIN DESCRIPTION:
END DESCRIPTION:
DSS Export Rating Curves= 0
DSS Export Rating Curve Sorted= 0
DSS Export Volume Flow Curves= 0
DXF OffsetX= 0
DXF OffsetY= 0
DXF ScaleX= 0
DXF ScaleY= 0

--- NancyFk.p01 (plan) ---

Plan Title=Floodplain
Program Version=4.00
Geom File=g01
Flow File=f01
K Sum by GR=0
Std Step Tol=0.01
Critical Tol=0.01
Num of Std Step Trials=20
Max Error Tol=0.3
Flow Tol Ratio=0.001
Split Flow NTrial=30
Split Flow Tol=0.02
Split Flow Ratio=0.02
Log Output Level=0
Friction Slope Method=1
Unsteady Friction Slope Method=2
Unsteady Bridges Friction Slope Method=1
Global Log Level=0
CheckData=False
Run HTab=0
Run UNet=0
Run PostProcess=0
UNET Theta=0
UNET Theta Warmup=0
UNET ZTol=0
UNET ZSATol=0
UNET MxIter=0
UNET MaxInSteps=0
UNET DtIC=0
UNET DtMin=0
UNET MaxCRTS=0
UNET WFStab=0
UNET SFStab=0
UNET WFX=0
UNET SFX=0
UNET DSS MLevel=0
UNET DZMax Abort=0
UNET Convert EG Bridges=0
UNET Use Existing IB Tables=0
UNET Froude Limit=0
UNET Froude Power=0
Write IC File=0
Echo Input=False
Echo Output=False
Write Detailed=0

--- NancyFk.f01 (steady flow) ---

Flow Title=NFF Regression Equation
Program Version=4.00
Number of Profiles=1
Profile Names=P100yr
River Rch & RM=NancyFk,Main      ,12301.1
767.3548
River Rch & RM=NancyFk,Main      ,10853.1
838.0121
River Rch & RM=NancyFk,Main      ,9229.8
911.6259
River Rch & RM=NancyFk,Main      ,8021.3
963.8655
River Rch & RM=NancyFk,Main      ,6509.7
1050.146
River Rch & RM=NancyFk,Main      ,3741.8
1124.480
River Rch & RM=NancyFk,Main      ,2068.2
1226.860
River Rch & RM=NancyFk,Main      ,251.9
1265.322
Boundary for River Rch & Prof#=NancyFk,Main      ,1
Up Type=0
Dn Type=3
Dn Slope=0.015573

--- NancyFk.g01 (geometry) ---

Geom Title=USGS 10m DEM
Program Version=4.00

River Reach=NancyFk         ,Main
Reach XY= 30
     1808512.679       193593.72     1808191.481      193186.586
      1808056.27      193154.817     1807939.702      192989.983
     1807665.584      192813.308     1807675.198      192677.862
     1807434.268      192353.409     1807403.131      192120.613
     1807298.575      192008.257     1807221.166      191572.036
     1806150.193      190796.127     1806088.266      190481.938
     1805550.958      189859.025     1805299.607      189408.233
     1804661.212      189142.311     1804341.984      188668.642
     1804217.706      188581.325     1804010.068      188537.612
     1803790.834      188588.765     1803113.037      188357.295
     1802943.648      188431.061     1802415.447      188405.562
     1802338.038      188476.595     1802139.508      188479.327
     1801955.548      188779.856      1801628.61      189034.849
     1801368.152      188822.658     1800776.061      188779.391
     1800190.628      188337.259     1799898.091      188333.217

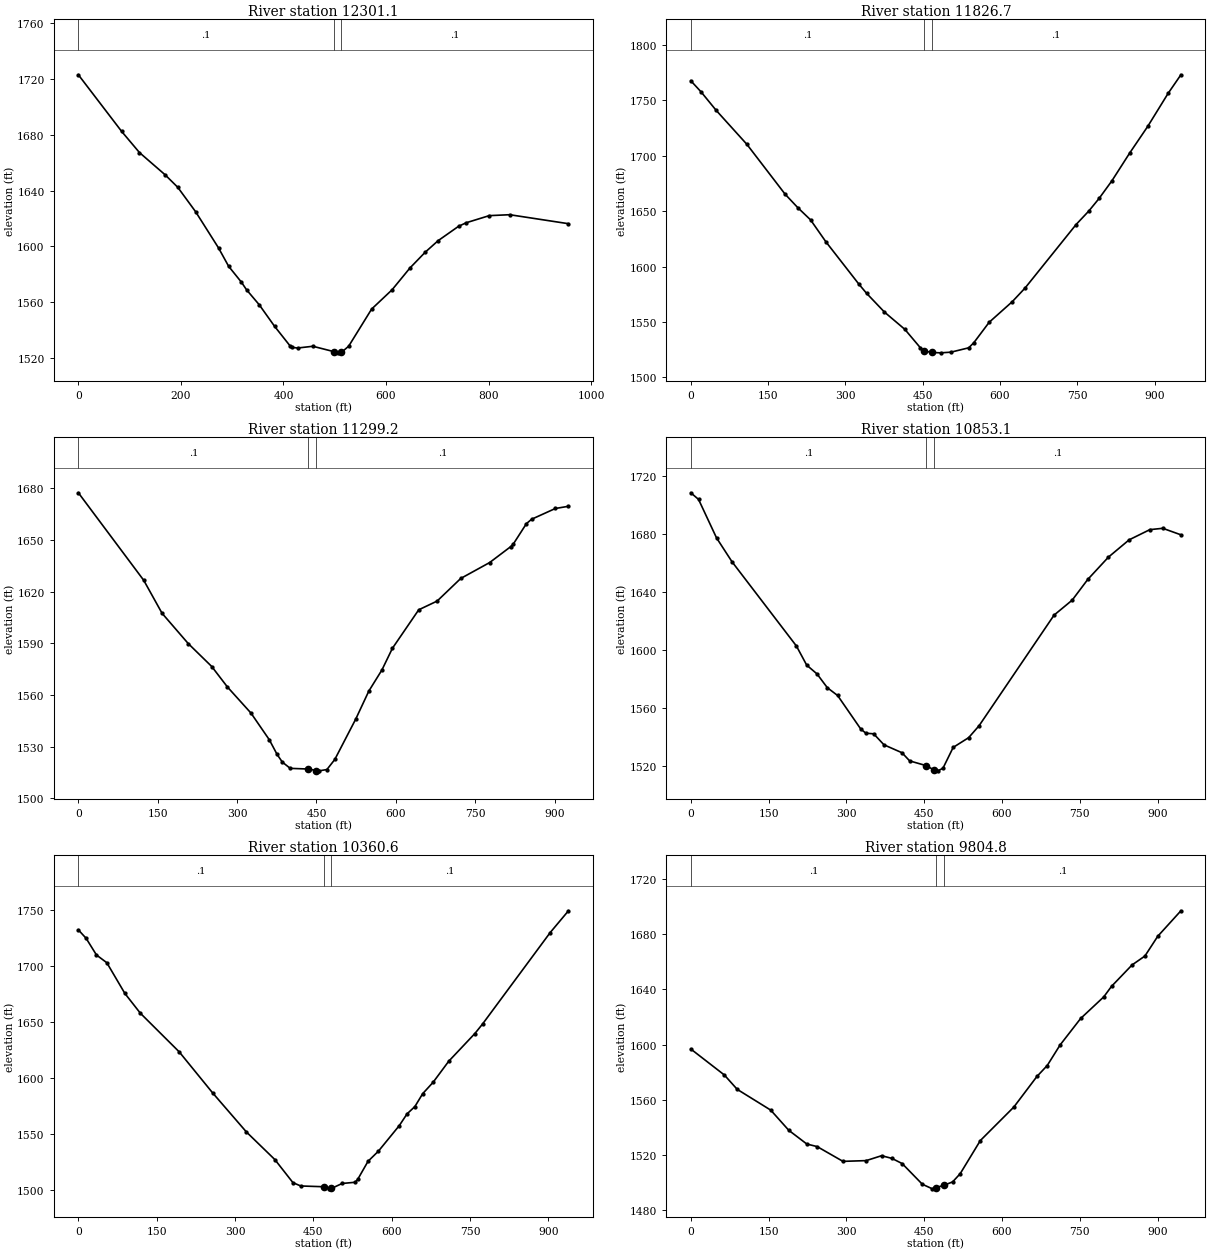
Type RM Length L Ch R = 1 ,12301.1 ,481.2,474.4,464.3
XS GIS Cut Line= 4
     1808749.691      193137.257      1808585.88      193488.474
     1808435.097      193594.581      1808376.18      193973.823
#Sta/Elev= 30
       0 1722.87    84.5 1682.27   119.2 1667.15   168.9 1651.34   193.8 1642.32
   228.6 1624.84   273.3  1598.9   293.1  1585.7     318 1574.34   327.9 1568.95
   352.8 1558.14   382.6 1542.77   412.5 1528.88   417.4 1527.66   427.4 1527.21
   457.3 1528.46   497.8 1524.67   507.1 1523.76   512.8 1524.05   527.1 1528.51
   571.9 1555.12   611.8 1568.93   646.7 1584.56   676.6  1595.9   701.5 1604.07
   741.4 1614.37   756.3 1616.91   801.2    1622   841.1 1622.67   955.7 1616.23
#Mann= 3 , 0 , 0
       0      .1       0   497.8    .045       0   512.8      .1       0
Bank Sta=497.8,512.8
XS Rating Curve= 0 ,0
Exp/Cntr=0.3,0.1

Type RM Length L Ch R = 1 ,11826.7 ,523.6,527.5,534.5
XS GIS Cut Line= 3
     1808354.261      192769.378     1808232.192      193166.432
     1807913.392      193597.019
#Sta/Elev= 30
       0 1767.57    19.8  1757.6    49.4 1740.78   108.8 1710.25     183 1665.28
   207.7 1653.08   232.4 1642.12   262.1 1622.37   326.4 1584.01   341.2 1575.83
   375.8 1558.95   415.4 1543.36   445.2 1526.92   452.4 1523.99   467.4 1522.51
   484.8 1522.17   504.7 1522.76   539.4 1526.71   549.3 1531.31   579.1 1549.75
   623.8 1568.27   648.6 1580.55   747.8 1637.92   772.6 1650.15   792.4 1661.42
   817.2 1677.27   851.9 1702.46   886.7 1726.32   926.4 1756.21   951.2 1772.96
#Mann= 3 , 0 , 0
       0      .1       0   452.4    .045       0   467.4      .1       0
Bank Sta=452.4,467.4
XS Rating Curve= 0 ,0
Exp/Cntr=0.3,0.1

Type RM Length L Ch R = 1 ,11299.2 ,446.3,446,445.8
XS GIS Cut Line= 4
     1808150.831      192627.258      1807861.75      192859.282
      1807725.86      193010.065     1807524.167      193299.268
#Sta/Elev= 30
       0 1677.45   123.6 1626.58   158.2 1607.45   207.6 1589.88   252.1 1576.53
   281.7 1564.65   326.2  1549.5   360.8 1534.02   375.6 1525.46   385.5 1521.01
   400.4 1517.38   434.6 1516.99   449.6 1516.12   454.8 1515.94   469.7 1516.69
   484.6 1522.53   524.2 1546.01   548.9 1562.26   573.7 1574.54   593.5 1587.12
   643.2 1609.47     678 1614.55   722.6 1627.68   777.3 1636.93     817 1646.15
     822 1647.69   846.8 1659.55   856.7  1662.1   901.4 1668.32   926.2 1669.61
#Mann= 3 , 0 , 0
       0      .1       0   434.6    .045       0   449.6      .1       0
Bank Sta=434.6,449.6
XS Rating Curve= 0 ,0
Exp/Cntr=0.3,0.1

Type RM Length L Ch R = 1 ,10853.1 ,476.3,492.5,496.4
XS GIS Cut Line= 4
     1807906.288      192262.473     1807625.338      192550.271
     1807550.877        192635.9     1807169.922      192833.395
#Sta/Elev= 30
       0  1708.6    14.9 1704.04    49.6 1677.47    79.4 1661.02   203.6 1602.86
   223.4 1589.68   243.3 1583.61   263.2 1574.08     283 1568.72   327.7 1545.55
   337.6 1542.68   352.5 1542.29   372.4 1534.69   407.1 1529.22   421.9 1523.59
     454  1520.3     469 1517.28   476.2 1516.73   486.1 1518.52   505.8 1532.91
   535.6 1539.62   555.6  1547.8   700.3 1624.19   735.2 1634.51   765.2 1648.79
   805.1 1664.21     845 1676.13   884.9 1683.16   909.8 1684.09   944.8 1679.59
#Mann= 3 , 0 , 0
       0      .1       0     454    .045       0     469      .1       0
Bank Sta=454,469
XS Rating Curve= 0 ,0
Exp/Cntr=0.3,0.1

Type RM Length L Ch R = 1 ,10360.6 ,558.8,555.8,548.5
XS GIS Cut Line= 4
     1807852.777      192131.753     1807448.494       192168.66
     1807323.772       192217.06     1806925.198      192228.883
#Sta/Elev= 30
       0 1731.88    14.8  1724.4    34.7 1709.48    54.5  1702.6    89.1 1675.19
   118.8 1657.54   193.1 1623.14   257.4  1586.4   321.8 1551.72   376.3 1527.09
   410.9 1506.54   425.8 1503.58   469.7 1502.89   480.3 1501.02   484.7 1501.38
   505.1  1505.8   529.8 1506.87   534.8 1509.36   554.7 1525.57   574.6 1534.61
   614.5 1557.36   629.5 1567.89   644.4 1574.36   659.4 1585.88   679.3 1595.99
   709.2 1614.76   759.1 1639.37     774 1647.96   903.6 1729.53   938.5  1748.9
#Mann= 3 , 0 , 0
       0      .1       0   469.7    .045       0   484.7      .1       0
Bank Sta=469.7,484.7
XS Rating Curve= 0 ,0
Exp/Cntr=0.3,0.1

Type RM Length L Ch R = 1 ,9804.8  ,247.4,243.1,239
XS GIS Cut Line= 4
      1807701.66       191714.45     1807299.573      191693.974
     1807165.544       191762.85     1806794.283      191886.958
#Sta/Elev= 30
       0 1596.73    64.6 1577.89    89.5 1567.42   154.1 1552.34   188.9 1537.67
   223.7  1527.7   243.6 1525.85   293.3 1515.12     338 1515.66   367.8 1519.23
   387.7 1517.28   407.5  1513.5   446.4 1498.47   465.8 1495.16   473.3 1496.11
   488.3  1497.8   504.7  1500.2   519.3 1506.16   558.2 1530.26   622.7 1554.56
   667.3 1576.82   687.1 1584.74   711.9 1599.67   751.5  1618.9   796.1 1634.62
     811 1642.24   850.6 1657.79   875.4 1664.28   900.2 1678.65   944.8 1697.15
#Mann= 3 , 0 , 0
       0      .1       0   473.3    .045       0   488.3      .1       0
Bank Sta=473.3,488.3
XS Rating Curve= 0 ,0
Exp/Cntr=0.3,0.1

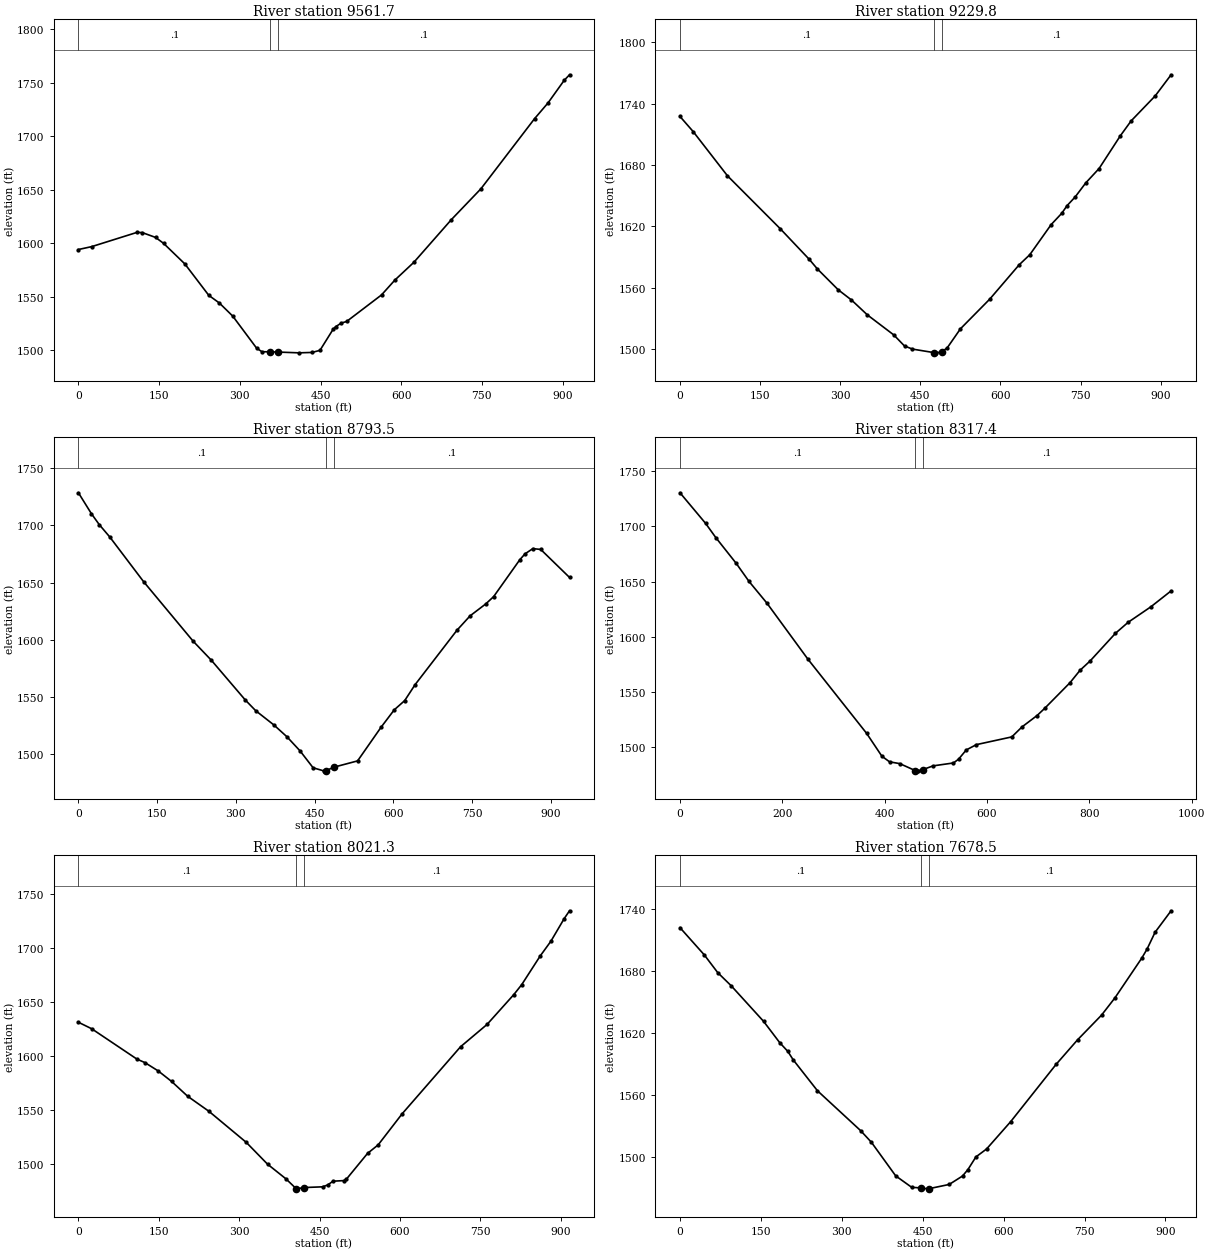
Type RM Length L Ch R = 1 ,9561.7  ,334.1,331.9,331.2
XS GIS Cut Line= 4
      1807455.94      191334.701     1807171.128      191513.407
     1807066.883      191602.759     1806653.627      191751.681
#Sta/Elev= 30
       0 1594.04    24.7 1596.75   108.8 1610.03   118.7 1609.86   143.4 1605.34
   158.2 1599.84   197.8 1580.61   242.3 1551.25   262.1 1544.02   286.8 1531.86
   331.3 1501.84   341.1 1498.57   356.9 1498.45   371.9 1498.23   409.8 1497.52
   434.3  1497.9     449 1499.86   473.5  1519.6   478.5 1522.07   488.5 1525.31
   498.5 1526.81   563.4 1551.63   588.3 1565.54   623.3 1581.99   693.2 1621.96
   748.1 1650.76   847.9 1716.31   872.9 1731.01   902.8 1752.02   912.8 1757.28
#Mann= 3 , 0 , 0
       0      .1       0   356.9    .045       0   371.9      .1       0
Bank Sta=356.9,371.9
XS Rating Curve= 0 ,0
Exp/Cntr=0.3,0.1

Type RM Length L Ch R = 1 ,9229.8  ,438.4,436.3,434.2
XS GIS Cut Line= 3
     1807185.658       190993.89     1806958.916      191299.332
     1806575.194      191678.201
#Sta/Elev= 30
       0  1727.4    24.7 1712.65    88.9 1669.45   187.7 1617.79   242.1 1587.84
   256.9  1578.7   296.4 1558.07   321.1 1548.16   350.8 1533.64   400.4    1514
   420.4 1503.24   435.3  1500.2   475.1  1496.8   480.3 1496.54   490.1 1497.64
   500.2 1501.27   525.2 1520.04   580.1 1549.04     635 1582.47     655 1592.37
     695 1621.79   714.9 1632.87   724.9 1640.38   739.9 1648.75   759.9 1662.59
   784.8 1676.59   824.8 1708.72   844.8 1723.11   889.7 1747.42   919.6 1768.14
#Mann= 3 , 0 , 0
       0      .1       0   475.1    .045       0   490.1      .1       0
Bank Sta=475.1,490.1
XS Rating Curve= 0 ,0
Exp/Cntr=0.3,0.1

Type RM Length L Ch R = 1 ,8793.5  ,469.1,476.1,489.2
XS GIS Cut Line= 3
     1806703.391      190654.997     1806609.164      191040.887
     1806260.068      191450.291
#Sta/Elev= 30
       0 1728.58    24.8 1710.26    39.7 1700.71    59.6 1689.97   124.1  1650.8
   218.5 1598.67   253.2 1581.98   317.8 1547.21   337.6 1537.85   372.4  1525.3
   397.2 1514.98   422.1 1502.65     447 1487.85     467 1485.18   471.3 1485.27
   486.3 1488.35   531.7 1493.89   576.6 1523.47   601.5 1538.57   621.4 1546.67
   641.3 1560.67     721 1608.28     746 1620.87   775.8 1631.29   790.8 1637.68
   840.6 1669.95   850.6 1675.13   865.5 1679.71   880.5 1678.98   935.3 1654.48
#Mann= 3 , 0 , 0
       0      .1       0   471.3    .045       0   486.3      .1       0
Bank Sta=471.3,486.3
XS Rating Curve= 0 ,0
Exp/Cntr=0.3,0.1

Type RM Length L Ch R = 1 ,8317.4  ,293.9,296.1,293.5
XS GIS Cut Line= 3
     1806593.455       190548.08     1806120.297      190855.939
       1805726.2      190887.239
#Sta/Elev= 30
       0 1730.54      50 1702.83    69.9 1689.97   109.9 1666.53   134.9 1650.17
   169.8 1630.54   249.8  1579.8   364.7 1512.44   394.6 1491.68   409.6 1486.58
   429.6 1484.96   459.7 1478.68   464.6 1478.42   474.7 1479.56   494.6 1482.92
   534.5 1485.57   544.5 1489.03   559.5 1497.37   579.3 1502.19   648.5 1509.19
   668.3  1518.2   697.9 1528.58   712.8  1535.1   762.2 1558.31   781.9 1569.61
   801.7 1578.12   851.1 1603.14   875.8 1613.08   920.3 1627.16   959.8 1641.58
#Mann= 3 , 0 , 0
       0      .1       0   459.7    .045       0   474.7      .1       0
Bank Sta=459.7,474.7
XS Rating Curve= 0 ,0
Exp/Cntr=0.3,0.1

Type RM Length L Ch R = 1 ,8021.3  ,345.6,342.8,340
XS GIS Cut Line= 4
     1806474.846      190363.349     1806155.171      190534.811
     1806067.987      190597.293     1805634.973       190704.82
#Sta/Elev= 30
       0 1630.84    24.8 1624.81   109.3 1596.67   124.2 1593.44   149.1 1585.68
   173.9    1576   203.7 1562.34   243.5 1548.36   313.1 1519.62   352.8 1499.42
   387.1 1485.84   406.2 1476.74   406.6 1476.55   421.2 1477.75   455.4 1478.41
   465.1 1480.16     475 1483.63   494.8 1484.17   499.8  1485.4   539.4 1509.37
   559.2 1517.26   603.9 1546.02   712.9 1608.14   762.5 1628.89   812.1 1656.35
     827 1665.65   861.6 1692.29   881.5 1705.91   906.3 1726.86   916.2 1734.09
#Mann= 3 , 0 , 0
       0      .1       0   406.2    .045       0   421.2      .1       0
Bank Sta=406.2,421.2
XS Rating Curve= 0 ,0
Exp/Cntr=0.3,0.1

Type RM Length L Ch R = 1 ,7678.5  ,476.7,476.4,476.1
XS GIS Cut Line= 3
     1806270.527      190016.835     1805950.288       190264.54
     1805571.763      190599.783
#Sta/Elev= 30
       0  1722.2      45 1695.85      70 1678.63      95 1665.88     155 1631.44
   184.9 1610.82   199.9 1602.37   209.9 1594.17   254.9 1564.22   334.9 1525.61
   354.9 1514.33   399.9 1481.82   429.6  1470.7   446.6 1470.14   459.4 1469.24
   461.6  1469.4     499 1473.47   523.8 1481.65   533.8 1487.88   548.6 1500.14
   568.4 1507.84   613.1 1534.31   697.3 1589.79     737 1613.51   781.6 1637.51
   806.4 1654.21     856 1692.58   865.9 1701.39   880.8 1717.73   910.5 1738.54
#Mann= 3 , 0 , 0
       0      .1       0   446.6    .045       0   461.6      .1       0
Bank Sta=446.6,461.6
XS Rating Curve= 0 ,0
Exp/Cntr=0.3,0.1

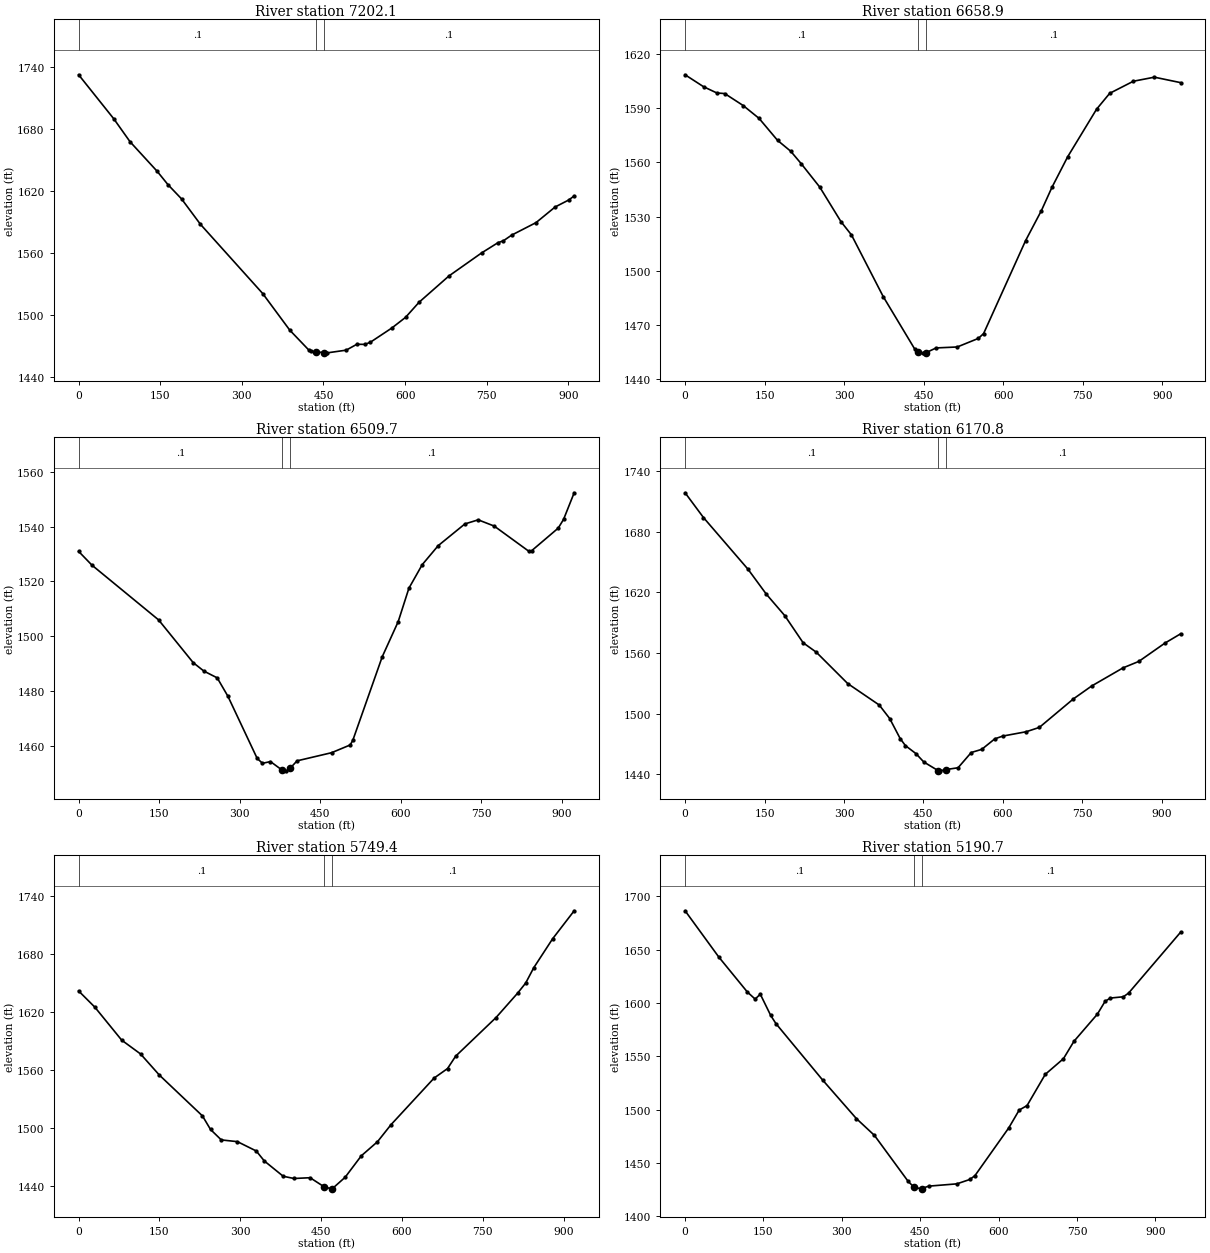
Type RM Length L Ch R = 1 ,7202.1  ,537.2,543.3,549.3
XS GIS Cut Line= 4
     1805937.791      189624.623     1805661.128      189889.649
     1805534.711      190007.347     1805258.133      190229.738
#Sta/Elev= 30
       0 1732.82    64.7 1690.11    94.5 1667.95   144.3 1639.35   164.2 1626.38
   189.1 1612.63   223.9 1587.96   338.3 1520.93   388.1 1485.42   422.6 1466.43
   427.5 1464.83   436.5 1464.25   451.5 1463.77   457.2 1463.46   491.7 1466.05
   511.4 1471.76   526.2 1471.65   536.1 1473.69   575.8 1487.56   600.8 1497.79
   625.8 1512.51   680.8    1538   740.8  1560.3   770.8 1570.18   780.8 1572.04
   795.8 1577.46   840.8 1589.64   875.8 1604.76   900.8 1611.52   910.8 1615.47
#Mann= 3 , 0 , 0
       0      .1       0   436.5    .045       0   451.5      .1       0
Bank Sta=436.5,451.5
XS Rating Curve= 0 ,0
Exp/Cntr=0.3,0.1

Type RM Length L Ch R = 1 ,6658.9  ,164.8,149.1,133.5
XS GIS Cut Line= 4
     1805758.657      189300.455     1805406.841      189440.651
       1805268.8      189510.398      1804972.19      189780.947
#Sta/Elev= 30
       0 1608.59    34.9 1601.96    59.8 1598.52    74.8 1598.17   109.6 1591.53
   139.5 1584.43   174.4 1572.24   199.3 1566.19   219.3 1559.21   254.1 1546.29
     294 1527.19   313.9 1519.78   373.7 1485.64   433.6 1456.33   439.7 1454.83
   448.6 1454.44   454.7 1454.55   473.5 1457.16   513.4 1457.69   553.2 1462.44
   563.1 1465.12   642.4  1516.7   672.2 1533.33     692 1546.17   721.7 1563.13
   776.2  1589.5     801 1598.31   845.6 1605.01   885.3 1607.26   934.8 1604.23
#Mann= 3 , 0 , 0
       0      .1       0   439.7    .045       0   454.7      .1       0
Bank Sta=439.7,454.7
XS Rating Curve= 0 ,0
Exp/Cntr=0.3,0.1

Type RM Length L Ch R = 1 ,6509.7  ,346.2,339,331.7
XS GIS Cut Line= 4
     1805489.666      189087.555     1805262.987       189317.14
     1805197.599      189466.806      1804828.52       189700.75
#Sta/Elev= 30
       0 1530.95    24.8 1525.92   148.9 1505.94   213.4 1490.32   233.3 1487.24
   258.1 1484.77     278 1478.06   332.5 1455.36   342.4 1453.57   357.3  1454.2
   379.2 1451.05     387 1450.82   394.2 1451.83   406.8 1454.47   471.1 1457.44
   505.8 1460.27   510.8 1462.05   565.4 1492.46   595.2 1505.32   615.1  1517.5
   639.9  1526.1   669.7 1533.05   719.4 1540.98   744.2 1542.47     774 1540.19
   838.5 1530.99   843.5 1531.16   893.1 1539.43   903.1 1542.61   922.9 1552.35
#Mann= 3 , 0 , 0
       0      .1       0   379.2    .045       0   394.2      .1       0
Bank Sta=379.2,394.2
XS Rating Curve= 0 ,0
Exp/Cntr=0.3,0.1

Type RM Length L Ch R = 1 ,6170.8  ,400.6,421.3,442.1
XS GIS Cut Line= 4
     1805149.998      188821.588     1804930.235      189203.801
     1804920.063      189312.781     1804777.515      189670.935
#Sta/Elev= 30
       0 1718.49    34.7 1693.99   118.9 1642.84   153.6 1618.11   188.2 1597.05
   222.9 1570.19   247.7 1560.89   307.1 1529.86   366.6 1508.66   386.4 1495.27
   406.2 1475.43   416.1  1468.5   435.9 1460.62   450.8 1452.31   477.5 1443.88
   480.7 1443.57   492.5 1444.81   515.5 1446.62   540.4  1461.7   560.2 1464.81
   584.9 1475.21   599.8 1477.93   644.2 1482.24     669 1486.51   733.2 1514.67
   767.8 1527.46   827.1  1545.4   856.8 1551.76   906.2 1569.88   935.8 1579.06
#Mann= 3 , 0 , 0
       0      .1       0   477.5    .045       0   492.5      .1       0
Bank Sta=477.5,492.5
XS Rating Curve= 0 ,0
Exp/Cntr=0.3,0.1

Type RM Length L Ch R = 1 ,5749.4  ,571.5,558.7,546
XS GIS Cut Line= 3
     1804911.629       188709.98     1804628.357      189005.761
     1804198.881      189280.648
#Sta/Elev= 30
       0 1641.85      30  1625.1    79.9 1590.83   114.9  1576.5   149.8  1554.6
   229.8 1512.21   244.7  1498.2   264.7 1487.34   294.7 1485.53   329.6 1475.85
   344.6 1465.49   379.6 1449.63   399.6 1447.32   429.5 1448.13   455.9 1438.57
   469.5 1436.59   470.9 1436.85   494.5 1448.58   524.5 1470.84   554.5 1485.44
   579.5 1503.06   659.5 1551.46   684.5 1561.35   699.5 1574.16   774.5 1614.26
   814.5 1639.54   829.5 1650.05   844.5 1665.96   879.5 1695.98   919.5 1725.03
#Mann= 3 , 0 , 0
       0      .1       0   455.9    .045       0   470.9      .1       0
Bank Sta=455.9,470.9
XS Rating Curve= 0 ,0
Exp/Cntr=0.3,0.1

Type RM Length L Ch R = 1 ,5190.7  ,507,503.6,500.1
XS GIS Cut Line= 4
     1804472.285      188218.214     1804261.644      188572.244
     1804205.877      188687.159     1804009.557      189045.425
#Sta/Elev= 30
       0 1686.31    64.5 1642.93   119.1 1610.18     134 1603.54   143.9 1608.11
   163.8 1588.21   173.7 1580.62   263.1 1527.69   327.6 1491.58   362.3 1475.75
   426.7 1432.72   437.6 1427.36   451.3 1425.64   452.6 1425.89     466 1428.16
     520 1430.31   544.7 1434.41   554.6 1438.01   619.4 1482.84   639.3 1499.51
   654.3 1503.68   689.2 1532.98     724 1547.67     744 1563.91   788.8 1589.36
   803.7 1601.45   813.7 1604.49   838.6 1605.69   848.6 1609.14   948.2 1666.26
#Mann= 3 , 0 , 0
       0      .1       0   437.6    .045       0   452.6      .1       0
Bank Sta=437.6,452.6
XS Rating Curve= 0 ,0
Exp/Cntr=0.3,0.1

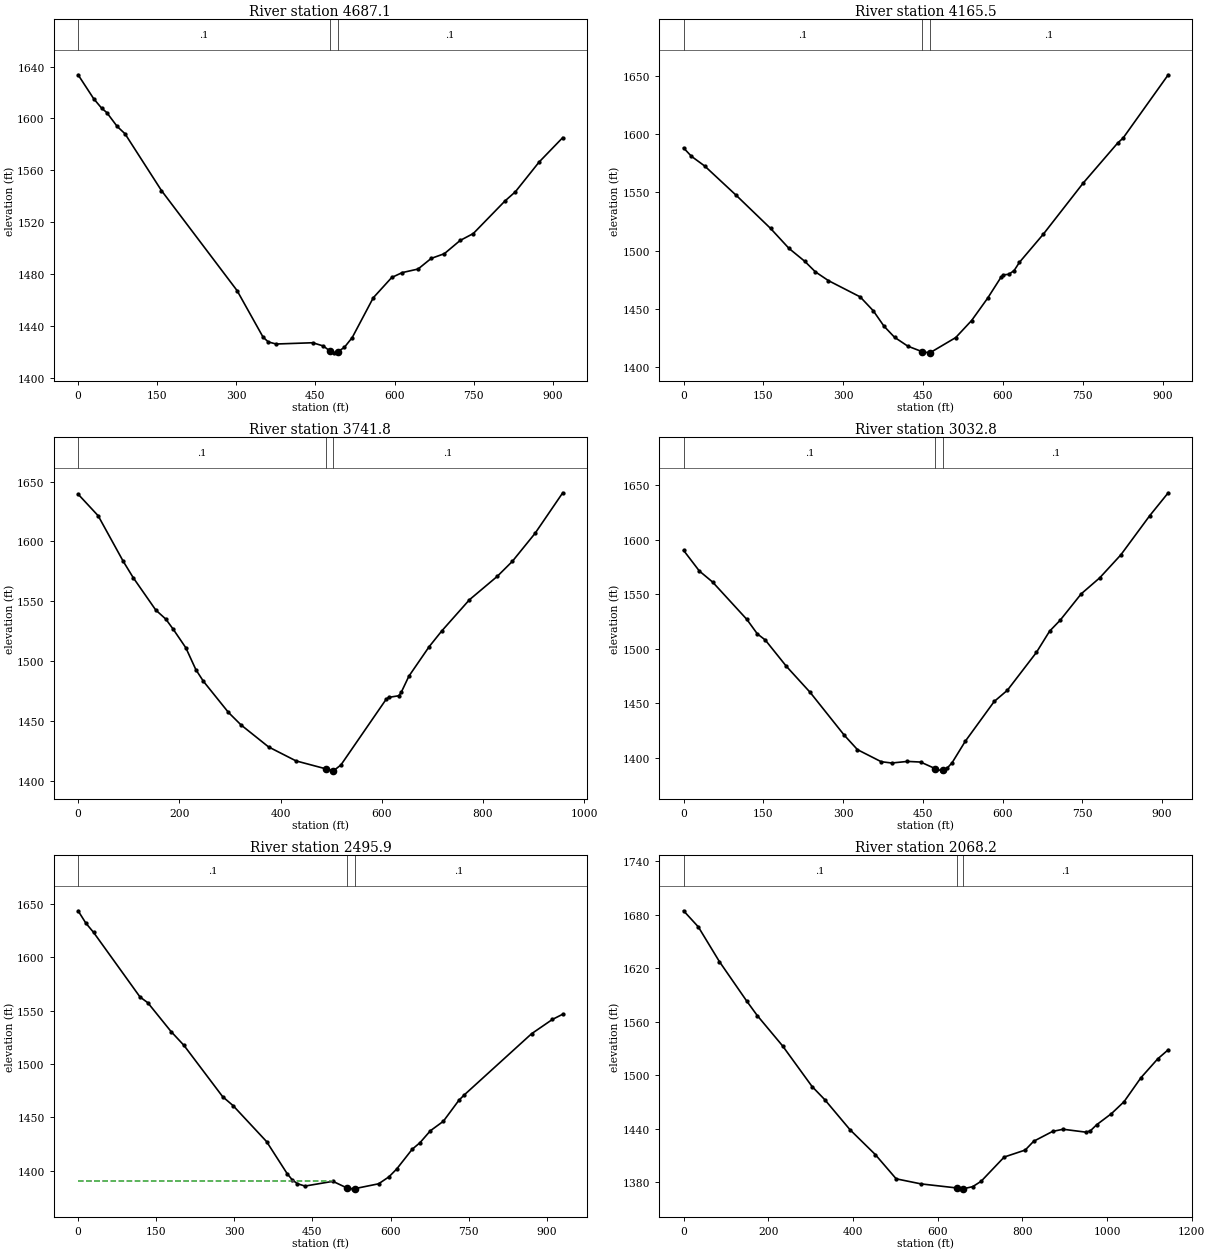
Type RM Length L Ch R = 1 ,4687.1  ,527.3,521.6,516
XS GIS Cut Line= 3
      1803855.26      188099.705     1803791.838      188509.855
      1803643.09      188991.424
#Sta/Elev= 30
       0 1633.65    29.6 1615.17    44.5 1607.96    54.4 1604.49    74.1 1593.81
    88.9 1588.17   158.1 1544.31   301.4 1467.16   350.8 1431.18   360.7 1427.51
   375.5  1425.9     445 1426.88   464.9 1424.38   477.1 1420.63   484.9 1419.09
   492.1 1419.86   504.8 1423.27   519.8 1430.88   559.7 1461.57   594.7 1477.23
   614.6 1481.01   644.6 1483.74   669.5 1491.94   694.5 1495.59   724.4 1505.79
   749.4 1511.15   809.3 1536.21   829.2 1543.38   874.1 1566.28     919 1585.18
#Mann= 3 , 0 , 0
       0      .1       0   477.1    .045       0   492.1      .1       0
Bank Sta=477.1,492.1
XS Rating Curve= 0 ,0
Exp/Cntr=0.3,0.1

Type RM Length L Ch R = 1 ,4165.5  ,416,423.7,426.5
XS GIS Cut Line= 3
     1803317.013      187979.145     1803279.284      188333.665
     1803256.339      188887.248
#Sta/Elev= 30
       0 1588.08    14.9 1580.85    39.6 1572.61      99 1547.38   163.4 1519.05
   198.1 1501.87   227.8 1490.78   247.6 1481.78   272.3 1474.21   331.8 1460.29
   356.5 1448.34   376.5  1435.2   396.4 1425.63   421.4 1417.99     448 1413.33
   461.3 1412.28     463 1412.34   511.3 1425.37   541.2 1440.01   571.2 1459.11
   596.1 1476.92   601.1  1479.2   611.1 1479.66   621.1 1482.91   631.1 1489.97
     676 1514.12   750.8 1557.92   815.7 1592.33   825.7 1596.49   910.6 1650.84
#Mann= 3 , 0 , 0
       0      .1       0     448    .045       0     463      .1       0
Bank Sta=448,463
XS Rating Curve= 0 ,0
Exp/Cntr=0.3,0.1

Type RM Length L Ch R = 1 ,3741.8  ,717.4,709.1,691.8
XS GIS Cut Line= 3
     1802854.643      187936.743     1802918.131       188327.78
     1802728.364      188843.136
#Sta/Elev= 30
       0 1639.48    39.6 1621.48    89.1 1583.52   108.9 1569.84   153.5  1542.8
   173.3 1535.28   188.2 1526.67   212.9 1511.32   232.7  1493.1   247.6  1483.4
   297.1 1457.41   321.9 1447.01   376.4 1428.64   430.6 1416.99   489.2  1410.4
   504.2 1408.71   504.5  1408.7   519.3  1413.6   608.7 1468.41   613.7 1469.97
   633.6 1471.33   638.6 1474.28   653.6 1487.65   693.5 1512.17   718.4  1525.3
   773.2 1551.38     828 1570.83   857.9 1583.36   902.8 1606.74   957.6 1640.62
#Mann= 3 , 0 , 0
       0      .1       0   489.2    .045       0   504.2      .1       0
Bank Sta=489.2,504.2
XS Rating Curve= 0 ,0
Exp/Cntr=0.3,0.1

Type RM Length L Ch R = 1 ,3032.8  ,540.4,536.8,528.1
XS GIS Cut Line= 4
     1802069.925       188061.61     1802277.083      188399.673
     1802321.018       188509.51     1802505.448      188860.774
#Sta/Elev= 30
       0 1590.36    29.7 1571.35    54.5 1561.28     119 1526.92   138.8 1513.58
   153.6 1508.02   193.3 1483.84   237.9 1459.96   302.3 1420.48   327.1 1407.23
   371.7 1396.17   391.5 1394.97   421.1 1396.44   445.8 1395.85   473.6 1389.75
   485.2 1387.78   488.6 1388.16   495.1 1389.93   504.9 1395.12   529.7 1414.86
   584.2 1451.49     609  1461.8   663.6 1496.58   688.4  1516.1   708.2 1526.11
   747.9  1550.4   782.6 1565.06   822.3 1586.15   876.8 1622.25   911.5 1643.23
#Mann= 3 , 0 , 0
       0      .1       0   473.6    .045       0   488.6      .1       0
Bank Sta=473.6,488.6
XS Rating Curve= 0 ,0
Exp/Cntr=0.3,0.1

Type RM Length L Ch R = 1 ,2495.9  ,413,427.8,442.5
XS GIS Cut Line= 4
     1801668.085      188334.854     1801893.653      188667.275
     1802019.466      188803.073     1802290.094      189015.425
#Sta/Elev= 30
       0  1643.5    14.9 1631.94    29.8 1623.22     119  1562.7   133.9 1557.35
   178.6 1530.35   203.3 1517.43   277.7 1469.32   297.6 1461.01     362 1427.29
   401.7 1397.11   411.5 1391.35   421.2 1387.84   435.8 1385.61   489.4 1390.05
   515.9 1383.95   528.4 1383.02   530.9 1383.15   577.1 1387.74   596.8 1394.18
   611.8 1401.55   641.7 1420.12   656.6 1426.24   676.6 1437.43   701.5 1446.32
   731.4 1466.01   741.4 1470.89     871 1528.35   910.9  1541.7   930.8 1546.61
#Mann= 3 , 0 , 0
       0      .1       0   515.9    .045       0   530.9      .1       0
#XS Ineff= 2 , 0
          489.81 1389.97
Permanent Ineff=
       F       F
Bank Sta=515.9,530.9
XS Rating Curve= 0 ,0
Exp/Cntr=0.3,0.1

Type RM Length L Ch R = 1 ,2068.2  ,654.7,657.4,673.5
XS GIS Cut Line= 4
     1801555.244      188383.918      1801640.03       188858.99
     1801663.994      189072.673      1801292.25      189320.759
#Sta/Elev= 30
       0 1684.52    34.8  1666.5    84.6 1627.58   149.2 1583.26   174.1 1567.02
   233.8 1533.08   303.5 1487.48   333.3 1472.84     393  1439.1   452.7 1411.26
   502.1 1384.01   560.8 1378.32   645.5 1373.77   658.5 1372.79   660.5 1372.84
   682.9 1375.26   702.6 1381.23   757.2 1408.45   806.8 1416.28   826.7 1426.11
   871.4 1437.16   896.2 1439.59   950.9 1436.28   960.8 1437.89   975.7 1444.72
  1010.4 1457.09  1040.2 1470.49    1080 1497.33  1119.7 1518.51  1144.5  1528.7
#Mann= 3 , 0 , 0
       0      .1       0   645.5    .045       0   660.5      .1       0
Bank Sta=645.5,660.5
XS Rating Curve= 0 ,0
Exp/Cntr=0.3,0.1

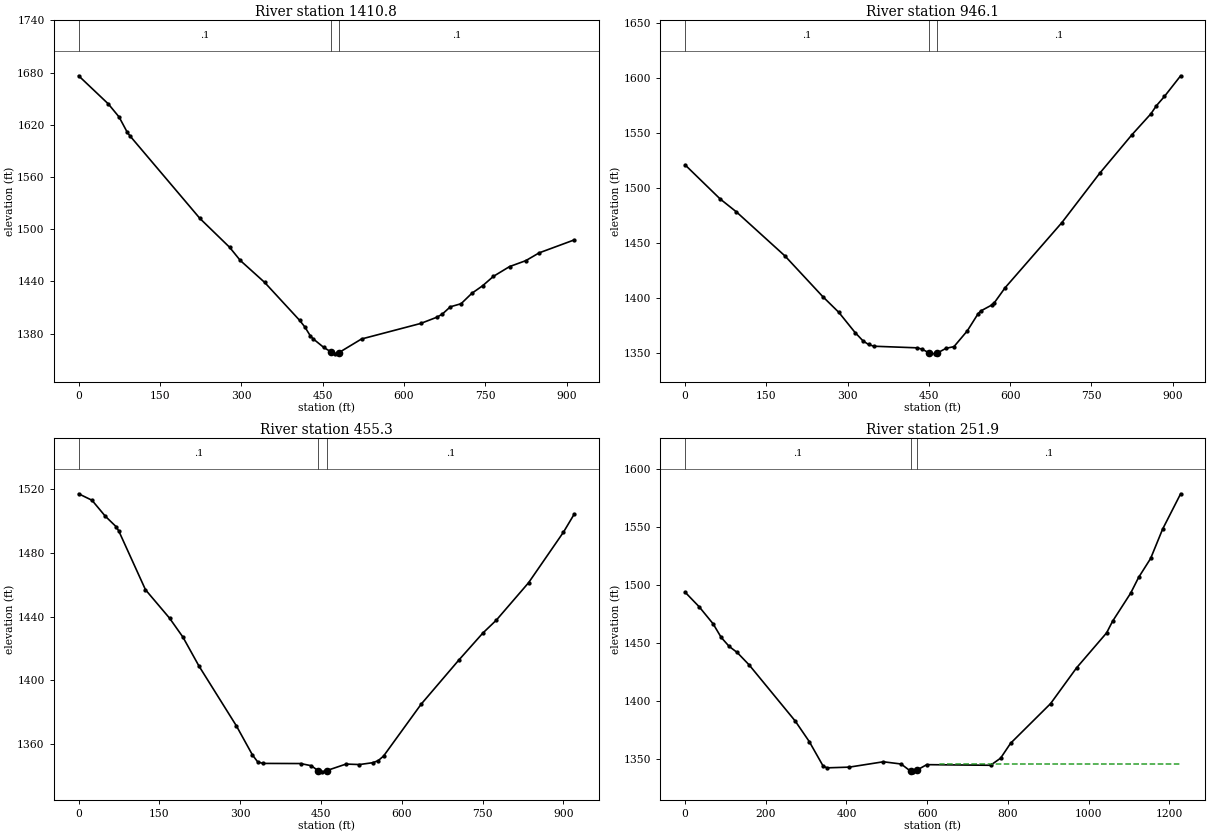
Type RM Length L Ch R = 1 ,1410.8  ,452.3,464.6,477
XS GIS Cut Line= 3
     1801160.511      188342.973     1801126.793      188749.153
     1801115.401      189255.519
#Sta/Elev= 30
       0  1676.3    54.7 1643.99    74.6 1628.95    89.5 1611.58    94.4 1607.42
   223.7 1512.33   278.4 1479.25   298.2 1464.04     343  1438.9   407.6 1395.26
   417.5 1387.43   427.4 1377.37   432.4 1374.09   452.3 1364.02   464.7  1359.3
   472.1 1356.72   479.7 1357.96   521.8 1373.78     631 1391.65   660.8  1398.8
   670.8 1402.37   685.6 1410.75   705.5 1414.34   725.4 1426.32   745.2 1434.95
   765.1 1445.75   794.9    1457   824.7 1463.78   849.5 1472.77   914.1 1487.64
#Mann= 3 , 0 , 0
       0      .1       0   464.7    .045       0   479.7      .1       0
Bank Sta=464.7,479.7
XS Rating Curve= 0 ,0
Exp/Cntr=0.3,0.1

Type RM Length L Ch R = 1 ,946.1   ,485.9,490.8,495.8
XS GIS Cut Line= 4
     1800908.832      188318.738     1800719.398      188669.272
     1800656.793      188768.685     1800444.201       189106.27
#Sta/Elev= 30
       0 1521.29    64.8 1490.26    94.6 1478.59   184.3 1438.51     254 1401.58
   283.9 1387.13   313.8 1368.83   328.7 1361.12   338.7 1357.94   348.6 1356.36
   427.8 1354.91   437.6 1353.72   450.3 1350.28   462.1 1349.44   465.3 1350.08
   481.7 1354.46   496.4 1355.98   520.9 1370.27   540.9 1385.89   545.8 1388.41
   565.8 1393.73   570.8 1395.81   590.7 1409.48   695.5 1468.71   765.3 1513.56
   825.1 1548.76     860 1567.74     870    1575     885 1583.54   914.9 1602.32
#Mann= 3 , 0 , 0
       0      .1       0   450.3    .045       0   465.3      .1       0
Bank Sta=450.3,465.3
XS Rating Curve= 0 ,0
Exp/Cntr=0.3,0.1

Type RM Length L Ch R = 1 ,455.3   ,222.6,203.3,184.1
XS GIS Cut Line= 3
      1800632.15      188116.401     1800246.102       188495.53
     1800043.595      188815.718
#Sta/Elev= 30
       0 1517.27    24.8 1513.19    49.6 1503.12    69.5  1496.6    74.5 1493.88
   124.1 1456.88   168.8 1438.99   193.6 1427.08   223.4 1408.86   292.9  1371.2
   322.7 1352.89   332.6 1348.47   342.5 1347.59     412 1347.51   431.9 1346.14
   445.2 1342.85   451.7 1342.29   460.2 1343.04   496.4 1347.18   521.2 1346.88
   546.1 1348.04     556 1349.32     566  1352.2   635.8 1384.85   705.6 1412.56
   750.4 1429.63   775.4 1437.75   835.2 1461.27     900 1493.11   919.9 1504.42
#Mann= 3 , 0 , 0
       0      .1       0   445.2    .045       0   460.2      .1       0
Bank Sta=445.2,460.2
XS Rating Curve= 0 ,0
Exp/Cntr=0.3,0.1

Type RM Length L Ch R = 1 ,251.9   ,251.4,251.9,252.3
XS GIS Cut Line= 4
     1800593.585       188072.16     1800138.262      188269.866
     1800142.256       188401.67     1799834.713      188916.904
#Sta/Elev= 30
       0 1493.81    34.8 1481.25    69.5  1466.5    89.4 1454.85   109.2 1447.07
   129.1 1441.84   158.8 1431.09     273 1382.73   307.8 1365.02   342.5  1343.7
   352.4 1342.39     407    1343   491.4 1347.61   535.5 1345.69   559.7 1339.29
   564.8 1338.94   574.7 1340.46     599 1345.14   757.2  1344.6     782 1350.72
   806.8 1363.56     906 1397.79   970.4 1428.61  1044.8 1458.73  1059.7 1468.81
  1104.3 1492.89  1124.2 1506.56  1153.9 1522.87  1183.7 1548.22  1228.3 1578.62
#Mann= 3 , 0 , 0
       0      .1       0   559.7    .045       0   574.7      .1       0
#XS Ineff= 2 , 0
          490.95 1347.46  631.86         1345.56
Permanent Ineff=
       F       F
Bank Sta=559.7,574.7
XS Rating Curve= 0 ,0
Exp/Cntr=0.3,0.1

Chan Stop Cuts=-1
Use User Specified Reach Order=0